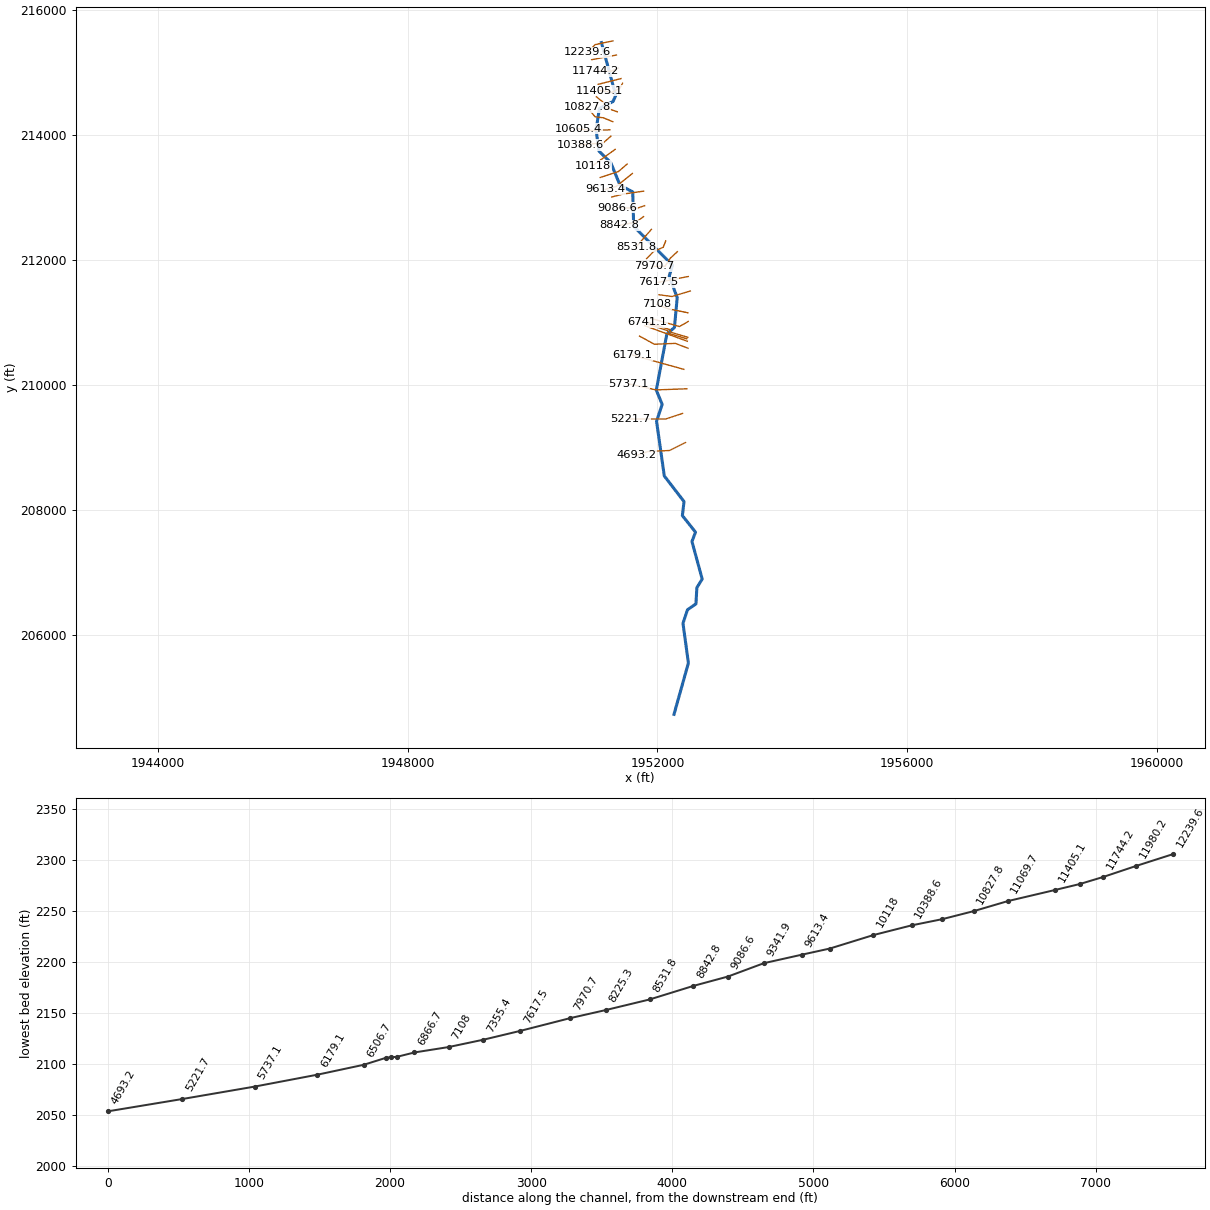
--- NFKMTNCK.prj (project) ---

Proj Title=NFKMTNCK
Current Plan=p01
Default Exp/Contr=0,0
English Units
Geom File=g01
Flow File=f01
Plan File=p01
BEGIN DESCRIPTION:
END DESCRIPTION:
DSS Export Rating Curves= 0
DSS Export Rating Curve Sorted= 0
DSS Export Volume Flow Curves= 0
DXF OffsetX= 0
DXF OffsetY= 0
DXF ScaleX= 0
DXF ScaleY= 0

--- NFKMTNCK.p01 (plan) ---

Plan Title=Floodplain
Program Version=4.00
Geom File=g01
Flow File=f01
K Sum by GR=0
Std Step Tol=0.01
Critical Tol=0.01
Num of Std Step Trials=20
Max Error Tol=0.3
Flow Tol Ratio=0.001
Split Flow NTrial=30
Split Flow Tol=0.02
Split Flow Ratio=0.02
Log Output Level=0
Friction Slope Method=1
Unsteady Friction Slope Method=2
Unsteady Bridges Friction Slope Method=1
Global Log Level=0
CheckData=False
Run HTab=0
Run UNet=0
Run PostProcess=0
UNET Theta=0
UNET Theta Warmup=0
UNET ZTol=0
UNET ZSATol=0
UNET MxIter=0
UNET MaxInSteps=0
UNET DtIC=0
UNET DtMin=0
UNET MaxCRTS=0
UNET WFStab=0
UNET SFStab=0
UNET WFX=0
UNET SFX=0
UNET DSS MLevel=0
UNET DZMax Abort=0
UNET Convert EG Bridges=0
UNET Use Existing IB Tables=0
UNET Froude Limit=0
UNET Froude Power=0
Write IC File=0
Echo Input=False
Echo Output=False
Write Detailed=0

--- NFKMTNCK.f01 (steady flow) ---

Flow Title=2010 USGS WV Regression Equation
Program Version=4.00
Number of Profiles=1
Profile Names=P100yr
River Rch & RM=NFKMTNCK,Main      ,12239.6
491.1460
River Rch & RM=NFKMTNCK,Main      ,11580.4
495.2753
River Rch & RM=NFKMTNCK,Main      ,11069.7
661.0460
River Rch & RM=NFKMTNCK,Main      ,10388.6
680.3738
River Rch & RM=NFKMTNCK,Main      ,8531.8
741.2927
River Rch & RM=NFKMTNCK,Main      ,7617.5
806.9634
River Rch & RM=NFKMTNCK,Main      ,7108
842.7466
River Rch & RM=NFKMTNCK,Main      ,4693.2
922.1428
River Rch & RM=NFKMTNCK,Main      ,1637.1
1021.011
River Rch & RM=NFKMTNCK,Main      ,221.9
1088.129
Boundary for River Rch & Prof#=NFKMTNCK,Main      ,1
Up Type=0
Dn Type=3
Dn Slope=0.016256

--- NFKMTNCK.g01 (geometry) ---

Geom Title=LiDAR
Program Version=4.10

River Reach=NFKMTNCK        ,Main
Reach XY= 30
     1951102.271      215472.018     1951330.978      214626.574
     1951289.046       214530.52     1951069.756      214417.369
     1951015.998       214077.64      1951063.22      213735.974
     1951251.415      213550.557     1951400.026      213190.141
     1951603.498      213083.196     1951618.679      212532.089
     1952240.998      211909.585     1952187.526      211734.585
     1952315.768      211391.238     1952271.554      210914.446
     1952149.332      210807.502     1951980.996      209911.499
     1952075.026      209683.196     1951984.815      209414.624
     1952109.054      208538.057     1952425.026      208128.335
     1952398.637      207903.335     1952609.054      207638.752
      1952552.11      207489.446     1952715.998      206888.752
     1952630.582      206750.557     1952615.999      206491.529
     1952480.154      206396.674      1952408.36      206179.724
     1952495.165      205545.696     1952264.609      204724.168

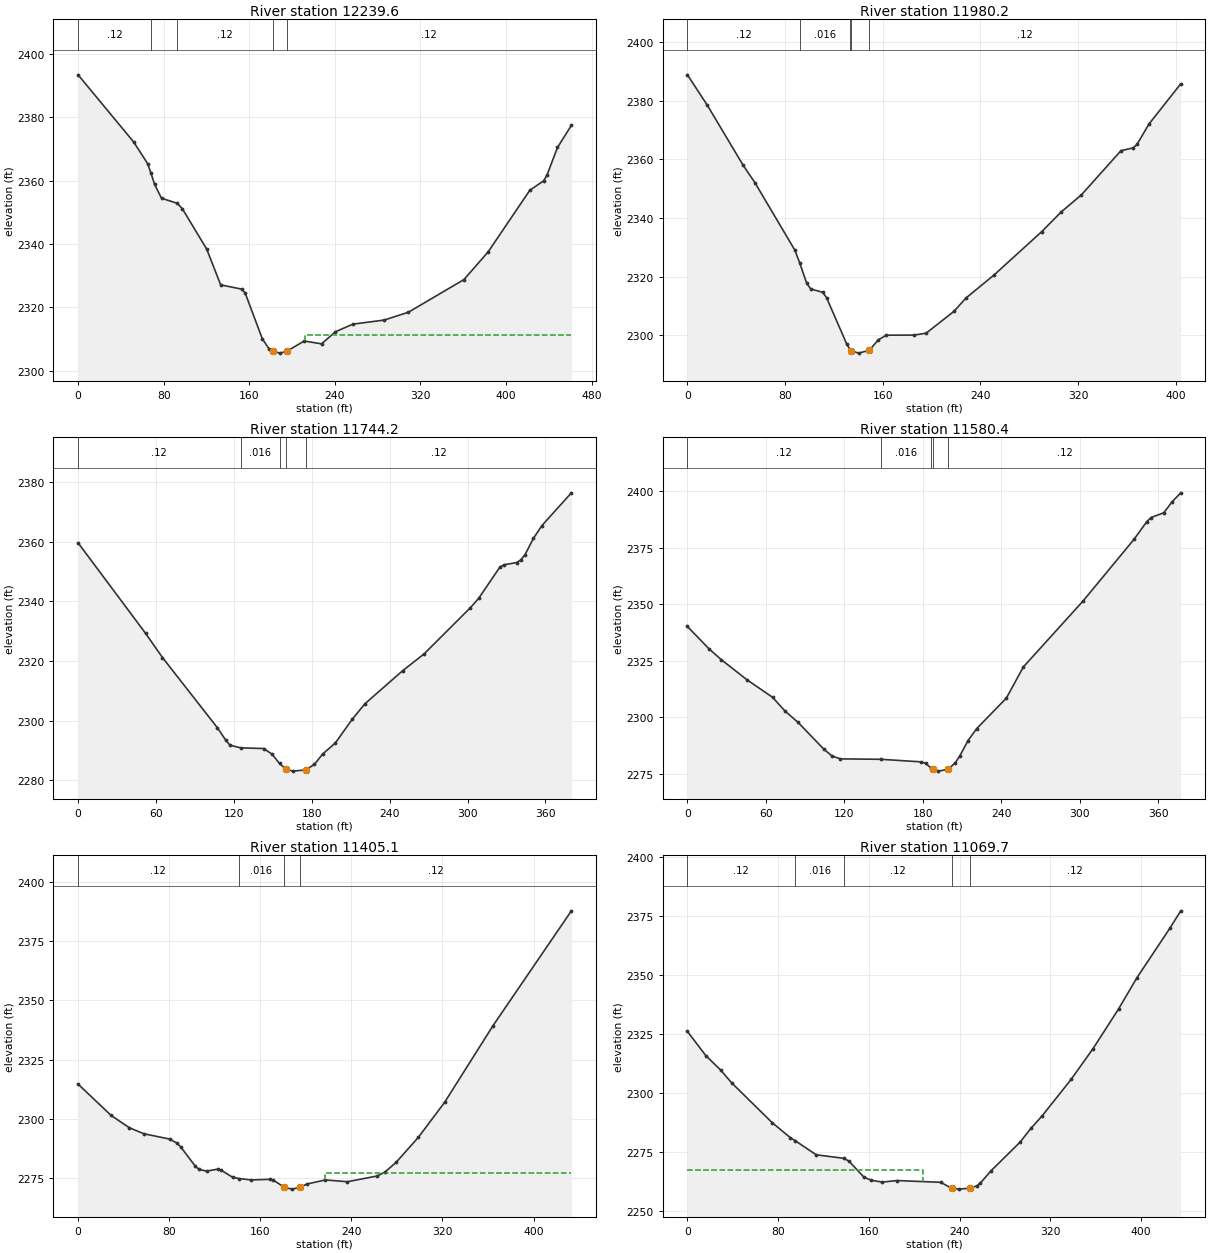
Type RM Length L Ch R = 1 ,12239.6 ,259.6,259.3,258.1
XS GIS Cut Line= 3
     1951287.727       215499.59     1951001.269      215439.695
     1950884.081      215318.601
#Sta/Elev= 30
       0 2393.37      52 2372.15      65 2365.34   68.252362.218    71.5  2358.8
      78  2354.4   92.752352.794    97.6 2351.03   120.3  2338.3   133.3 2327.05
   152.8 2325.71   156.1 2324.56   172.3 2309.97   178.8 2306.71   182.1 2306.11
   188.6 2305.49   195.1 2306.08   211.4 2309.31   227.6 2308.42   240.6 2312.24
   256.9 2314.64   286.2 2315.93   308.9 2318.42   360.7 2328.71   383.4 2337.48
   422.3 2356.91   435.2 2359.89   438.5 2361.82   448.2 2370.45   461.2 2377.41
#Mann= 5 ,-1 , 0
       0     .12       0   68.25    .016       0   92.75     .12       0
   182.1    .045       0   195.1     .12       0
#XS Ineff= 2 , 0
                          211.86         2311.11
Permanent Ineff=
       F       F
Bank Sta=182.1,195.1
XS Rating Curve= 0 ,0
Exp/Cntr=0.3,0.1

Type RM Length L Ch R = 1 ,11980.2 ,239.9,236,232.3
XS GIS Cut Line= 2
     1951342.415      215273.028     1950945.279      215198.809
#Sta/Elev= 30
       0 2388.84    16.3 2378.47    45.6 2358.04    55.4    2352      88 2329.07
   91.952324.738    97.7 2317.79     101 2315.86   110.8 2314.72     114 2312.83
   130.3 2297.24  133.282295.136   133.9 2294.84   140.1 2293.99   148.9 2294.94
   156.4 2298.54   162.9 2300.11   185.7 2300.14   195.5 2300.79   218.3 2308.23
   228.1 2312.77   250.9 2320.55     290 2335.34   306.3 2342.18   322.6 2347.91
   355.1 2363.01   364.9 2363.92   368.2 2365.14     378 2372.09     404 2385.78
#Mann= 5 ,-1 , 0
       0     .12       0   91.95    .016       0  133.28     .12       0
   133.9    .045       0   148.9     .12       0
Bank Sta=133.9,148.9
XS Rating Curve= 0 ,0
Exp/Cntr=0.3,0.1

Type RM Length L Ch R = 1 ,11744.2 ,158.4,163.8,169.3
XS GIS Cut Line= 3
     1951369.758      215064.695     1951257.779      215012.611
     1951001.269      215011.309
#Sta/Elev= 30
       0 2359.62      52 2329.26      65 2321.16   107.2 2297.67   113.8 2293.41
     117 2291.77  125.212290.872     143 2290.64   149.5 2288.71  155.16 2285.62
   160.3 2283.65   165.7 2283.06   175.3 2283.48     182  2285.3   188.4  2288.8
   198.2 2292.51   211.2 2300.47   220.9 2305.63   250.1 2316.77   266.4 2322.32
   302.1 2337.83   308.6 2341.03   324.8 2351.41   328.1 2352.26   337.8    2353
     341  2353.9   344.3 2355.66   350.8 2361.17   357.3 2365.42     380 2376.39
#Mann= 5 ,-1 , 0
       0     .12       0  125.21    .016       0  155.16     .12       0
   160.3    .045       0   175.3     .12       0
Bank Sta=160.3,175.3
XS Rating Curve= 0 ,0
Exp/Cntr=0.3,0.1

Type RM Length L Ch R = 1 ,11580.4 ,169.7,175.3,181
XS GIS Cut Line= 2
     1951416.633      214896.726     1951050.748      214804.278
#Sta/Elev= 30
       0 2340.12    16.3 2330.37      26 2325.41    45.6 2316.55    65.1 2308.85
    74.8 2302.67    84.6 2297.77   104.1 2286.06   110.6 2282.88   117.1 2281.62
  148.142281.434   178.9  2280.3   182.2 2279.64  186.132277.706  187.542277.099
     192 2276.21   199.5 2277.01     205 2279.98   208.2 2282.76   214.7 2289.73
   221.2 2294.94     244 2308.48     257 2322.26   302.6 2351.33   341.6 2378.59
   351.4 2386.42   354.6 2388.23   364.4 2390.36   370.9 2395.28   377.4 2399.17
#Mann= 5 ,-1 , 0
       0     .12       0  148.14    .016       0  186.13     .12       0
  187.54    .045       0   199.5     .12       0
Bank Sta=187.54,199.5
XS Rating Curve= 0 ,0
Exp/Cntr=0.3,0.1

Type RM Length L Ch R = 1 ,11405.1 ,374.1,335.4,296.6
XS GIS Cut Line= 4
     1951440.071      214821.205     1951399.706      214744.382
     1951268.196      214672.768     1951074.186       214705.32
#Sta/Elev= 30
       0 2314.65    28.9 2301.48      45 2296.25    57.8 2293.71    80.4 2291.47
    86.8 2289.77      90 2288.25   103.1 2279.93   106.3 2278.67   112.8 2277.97
   122.6 2278.79   125.8  2278.3   135.6 2275.38  140.882274.849   151.9 2274.24
   168.2  2274.5   171.4 2274.18   181.2 2271.11   187.7 2270.37   194.8 2271.11
   200.7 2272.49     217 2274.24   236.5  2273.5   262.8 2275.91   269.3 2277.52
   279.2 2281.61   298.8  2292.2   321.8 2306.91   364.4 2339.31   433.2 2387.69
#Mann= 4 ,-1 , 0
       0     .12       0  140.88    .016       0   181.2    .045       0
   194.8     .12       0
#XS Ineff= 2 , 0
                          217.23         2277.26
Permanent Ineff=
       F       F
Bank Sta=181.2,194.8
XS Rating Curve= 0 ,0
Exp/Cntr=0.3,0.1

Type RM Length L Ch R = 1 ,11069.7 ,216.3,241.8,266.6
XS GIS Cut Line= 4
     1951355.436      214365.476     1951162.727      214433.184
     1951131.477      214516.518       1951020.8      214605.059
#Sta/Elev= 30
       0 2326.14    16.2 2315.94    29.2 2309.86    38.9 2304.45    74.6 2287.62
    90.8 2281.18   95.122279.901   113.5 2273.97  138.292272.447   142.7 2271.14
   155.6 2264.53   162.1 2263.18   171.8 2262.42   184.8 2263.07   223.3 2262.32
   232.9 2259.83   239.2 2259.44   248.8 2259.81   255.1 2260.79   258.3    2262
   267.8 2267.25   293.3  2279.3   302.9 2285.16   312.6 2290.33   338.4 2305.91
   357.7  2318.9   380.2 2335.69   396.3 2348.82   425.3 2369.73     435 2377.17
#Mann= 5 ,-1 , 0
       0     .12       0   95.12    .016       0  138.29     .12       0
   232.9    .045       0   248.8     .12       0
#XS Ineff= 2 , 0
          207.95 2267.43
Permanent Ineff=
       F       F
Bank Sta=232.9,248.8
XS Rating Curve= 0 ,0
Exp/Cntr=0.3,0.1

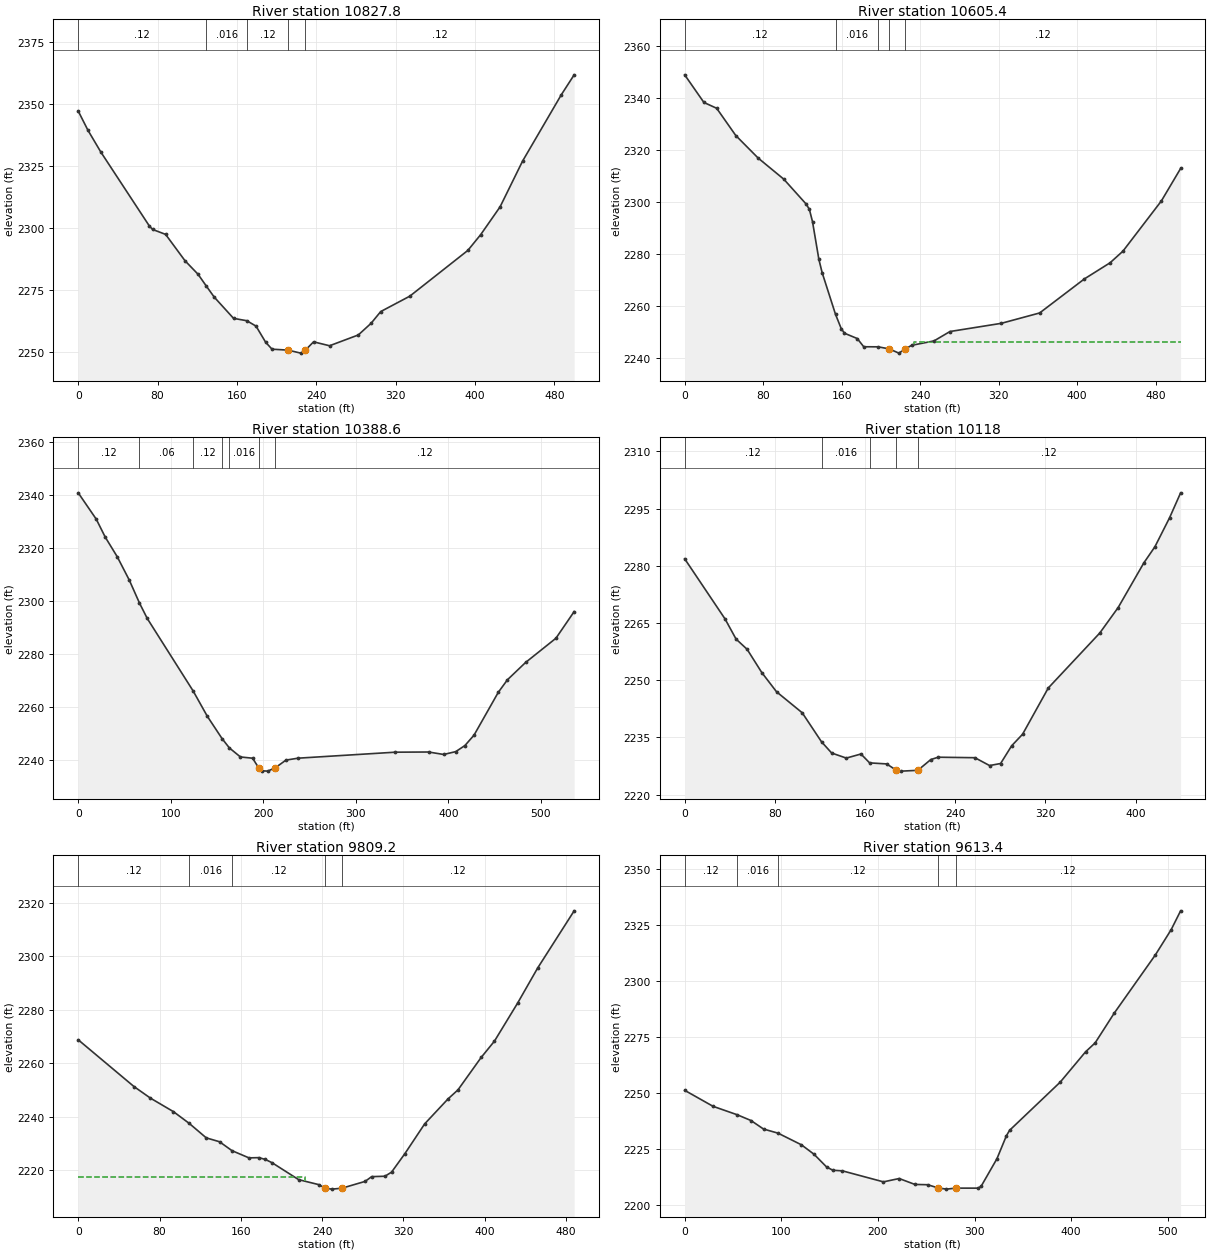
Type RM Length L Ch R = 1 ,10827.8 ,218.3,222.5,225.5
XS GIS Cut Line= 4
     1951284.255      214206.622     1951130.175      214269.556
     1951002.137      214283.662     1950869.758      214439.912
#Sta/Elev= 30
       0 2347.14     9.8  2339.4    22.8 2330.62    71.8 2300.77    75.1 2299.41
    88.1 2297.44   107.7  2286.8   120.8 2281.38   129.22276.579   137.1 2272.18
   156.6  2263.6  169.982262.647   179.3 2260.46     189 2253.96   195.4 2251.18
   211.5  2250.8   224.4 2249.59   229.1 2250.84   237.3 2254.14   253.4 2252.56
   282.4 2256.91   295.2 2261.58     305 2266.34   334.3 2272.54   392.8 2290.97
   405.8 2297.35   425.3 2308.52     448 2326.97     487 2353.67     500 2361.73
#Mann= 5 ,-1 , 0
       0     .12       0   129.2    .016       0  169.98     .12       0
   211.5    .045       0   229.1     .12       0
Bank Sta=211.5,229.1
XS Rating Curve= 0 ,0
Exp/Cntr=0.3,0.1

Type RM Length L Ch R = 1 ,10605.4 ,215.1,216.8,217.5
XS GIS Cut Line= 3
     1951236.512      214076.413     1950959.819      214064.478
      1950733.04      214092.689
#Sta/Elev= 30
       0 2348.78    19.6 2338.15    32.6 2335.92    52.1 2325.43    74.9 2316.76
     101 2308.65   123.8 2299.08   127.1 2297.04   130.3 2292.29   136.8 2277.76
   140.1 2272.71  153.732256.672   159.6 2251.13   162.9 2249.38   175.9 2247.34
   182.5 2244.18   197.12244.156   208.5 2243.36   218.3 2241.73   224.8 2243.31
   231.3 2244.73   254.1 2246.42   270.4 2250.04   322.7 2253.19   361.8 2257.18
   407.5  2270.3   433.6 2276.48   446.7 2280.95   485.9 2300.28   505.5 2312.76
#Mann= 5 ,-1 , 0
       0     .12       0  153.73    .016       0   197.1     .12       0
   208.5    .045       0   224.8     .12       0
#XS Ineff= 2 , 0
                          234.14         2246.18
Permanent Ineff=
       F       F
Bank Sta=208.5,224.8
XS Rating Curve= 0 ,0
Exp/Cntr=0.3,0.1

Type RM Length L Ch R = 1 ,10388.6 ,257.6,270.6,282.8
XS GIS Cut Line= 3
     1951253.873      213975.502     1951132.345       213868.08
     1950760.166      213834.443
#Sta/Elev= 30
       0 2340.73    19.5 2330.78    29.2 2324.01    42.2 2316.58    55.2 2307.77
   66.212299.105    74.6 2293.29  124.29 2265.86   139.5 2256.36  155.412247.947
  163.342244.412   175.3    2241   188.4 2240.53     195 2236.91   198.3 2235.78
   204.8 2235.65  212.992236.925   224.5 2239.81   237.6 2240.54   342.5  2242.8
   378.6 2242.87   394.9 2241.94     408 2243.02   417.9 2245.32   427.7 2249.23
   453.9 2265.39   463.8 2270.14   483.4 2276.67   516.2 2285.82   535.9 2295.89
#Mann= 7 ,-1 , 0
       0     .12       0   66.21     .06       0  124.29     .12       0
  155.41     .06       0  163.34    .016       0     195    .045       0
  212.99     .12       0
Bank Sta=195,212.99
XS Rating Curve= 0 ,0
Exp/Cntr=0.3,0.1

Type RM Length L Ch R = 1 ,10118   ,315.6,308.8,301.3
XS GIS Cut Line= 2
     1951321.509      213763.624     1950965.606      213504.943
#Sta/Elev= 30
       0 2281.84    35.8 2266.07    45.6 2260.78    55.4  2258.1    68.4 2252.01
    81.5 2246.96   104.3 2241.45  121.412233.838   130.4  2230.9   143.4 2229.57
   156.4 2230.64  164.082228.312   179.2 2228.04  187.812226.367   192.3 2226.15
  206.832226.357   218.4 2229.19   224.9  2229.8   257.5 2229.67   270.5 2227.61
   280.3 2228.15   290.1  2232.8   299.8 2235.83   322.6 2247.96   368.3 2262.38
   384.6 2269.06   407.4 2280.78   417.2    2285   430.2  2292.6     440 2299.14
#Mann= 5 ,-1 , 0
       0     .12       0  121.41    .016       0  164.08     .12       0
  187.81    .045       0  206.83     .12       0
Bank Sta=187.81,206.83
XS Rating Curve= 0 ,0
Exp/Cntr=0.3,0.1

Type RM Length L Ch R = 1 ,9809.2  ,187.6,195.8,203.9
XS GIS Cut Line= 3
     1951512.481      213527.513     1951375.329      213409.457
     1951083.662      213313.971
#Sta/Elev= 30
       0 2268.78    54.9 2251.28    71.1 2246.95    93.7  2241.9  109.232237.507
     126 2232.09     139 2230.65  151.292227.309     168 2224.61   177.7  2224.7
   184.2 2224.01   190.8 2222.78   216.9 2216.46   236.5 2214.62     243 2213.28
   249.5 2212.92   259.3 2213.25   282.2 2215.81   288.7 2217.59   301.8 2217.74
   308.3 2219.29   321.4 2226.21   340.9 2237.36   363.8 2246.66   373.6 2250.05
   396.4 2262.17   409.5 2268.29   432.4 2282.59     452 2295.64   487.9 2317.03
#Mann= 5 ,-1 , 0
       0     .12       0  109.23    .016       0  151.29     .12       0
     243    .045       0   259.3     .12       0
#XS Ineff= 2 , 0
          223.43  2217.5
Permanent Ineff=
       F       F
Bank Sta=243,259.3
XS Rating Curve= 0 ,0
Exp/Cntr=0.3,0.1

Type RM Length L Ch R = 1 ,9613.4  ,283.4,271.4,258.7
XS GIS Cut Line= 3
     1951597.551      213378.207     1951340.606       213171.61
     1951163.523      213122.999
#Sta/Elev= 30
       0 2251.16    29.4    2244   54.372240.231    68.6 2237.66    81.6 2233.85
   96.642231.999   120.8  2226.8   133.8  2222.6   146.9 2216.87   153.4 2215.41
   163.2 2215.15   205.7 2210.22     222 2211.71   238.3 2209.07   251.4 2208.94
   262.5 2207.49   270.9 2206.97   280.7 2207.42   303.6 2207.41   306.8 2208.22
   323.2 2220.57     333 2230.85   336.3 2233.28   388.7 2254.83     415 2268.42
   424.8 2272.35   444.5 2285.63   487.1 2311.68   503.5    2323   513.3 2331.44
#Mann= 5 ,-1 , 0
       0     .12       0   54.37    .016       0   96.64     .12       0
   262.5    .045       0   280.7     .12       0
Bank Sta=262.5,280.7
XS Rating Curve= 0 ,0
Exp/Cntr=0.3,0.1

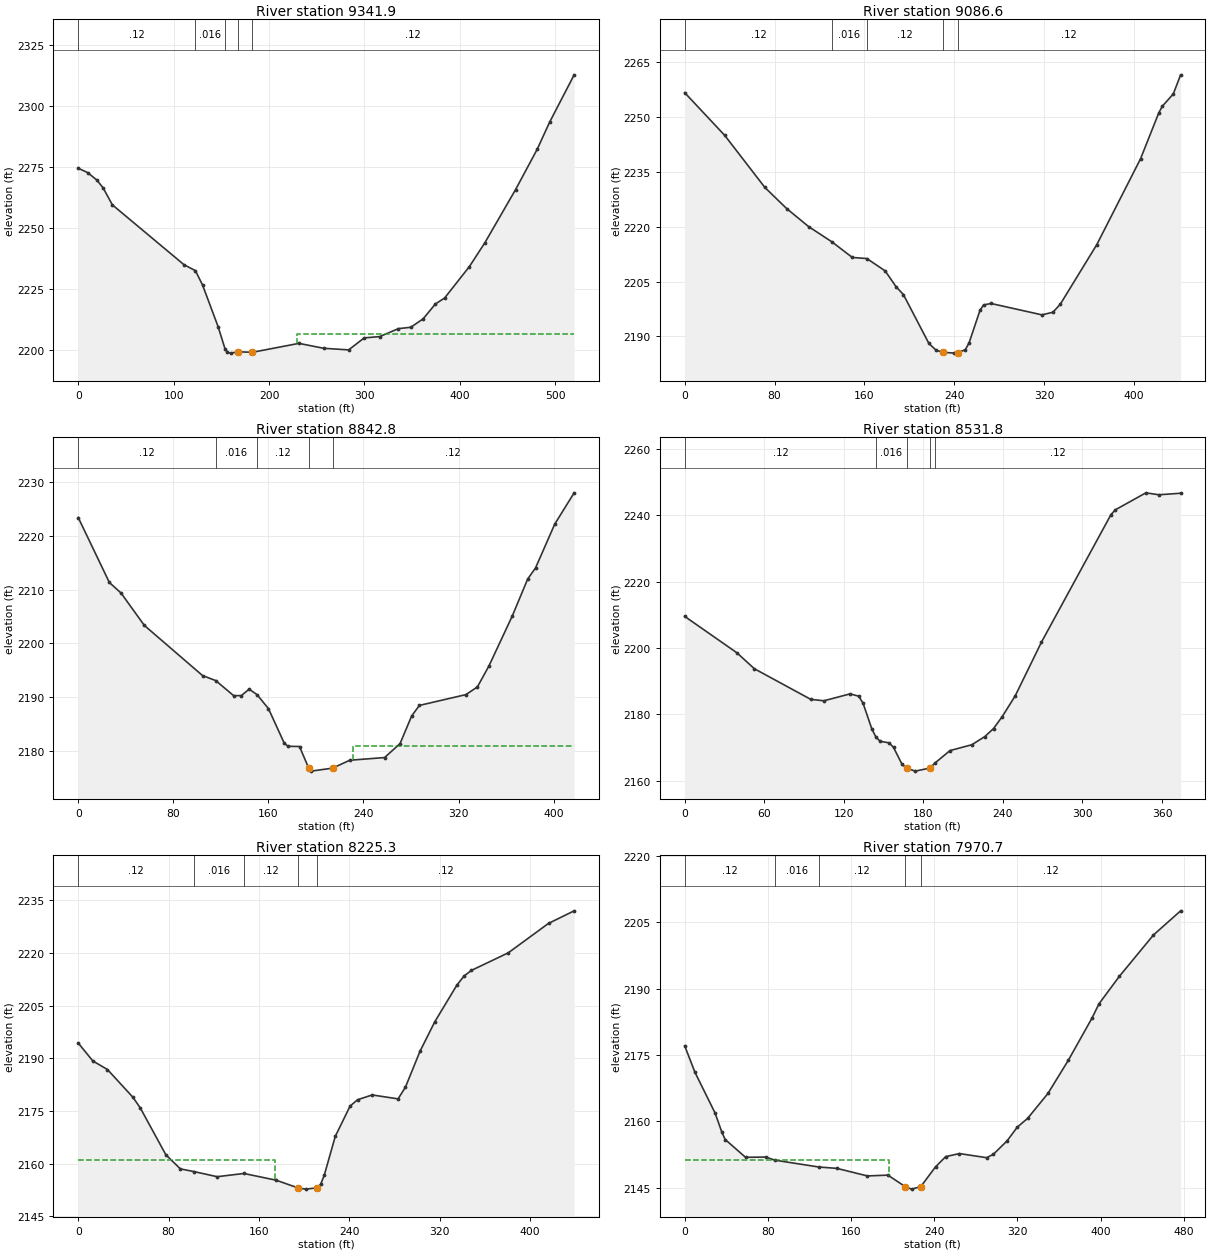
Type RM Length L Ch R = 1 ,9341.9  ,258,255.3,252
XS GIS Cut Line= 3
     1951778.106      213095.221     1951439.565       213046.61
      1951267.69      213001.471
#Sta/Elev= 30
       0 2274.37     9.8  2272.6    19.5 2269.54    26.1 2266.31    35.8 2259.35
   110.8 2234.83  122.832232.366   130.3 2226.48   146.6 2209.41  153.872200.294
   156.4 2198.83   159.6 2198.56   167.5  2199.1   182.5  2198.9   231.3 2202.56
   257.3 2200.54   283.4 2199.89   299.7 2204.81     316 2205.34   335.5  2208.6
   348.5 2209.16   361.4  2212.6   374.3 2218.71     384 2221.18   409.9 2234.04
     426 2243.73   458.3 2265.61     481 2282.16   493.9 2293.19   519.7 2312.67
#Mann= 5 ,-1 , 0
       0     .12       0  122.83    .016       0  153.87     .12       0
   167.5    .045       0   182.5     .12       0
#XS Ineff= 2 , 0
                           229.1         2206.25
Permanent Ineff=
       F       F
Bank Sta=167.5,182.5
XS Rating Curve= 0 ,0
Exp/Cntr=0.3,0.1

Type RM Length L Ch R = 1 ,9086.6  ,239,243.7,247.9
XS GIS Cut Line= 3
     1951793.731      212862.582     1951686.109      212826.369
     1951357.967       212827.86
#Sta/Elev= 30
       0 2256.62    35.7 2244.93    71.4 2230.72    90.8 2224.95   110.3 2220.03
  131.322215.799   149.3 2211.58  162.252211.276   178.5 2207.92   188.3 2203.57
   194.8 2201.44   217.5 2188.08     224  2186.2   230.5 2185.65   240.3 2185.43
   243.5 2185.55     250 2186.39   253.3 2188.24     263 2197.11   266.2 2198.59
   272.8    2199   318.2 2195.89     328 2196.61   334.5 2198.78     367 2215.06
     406 2238.54   422.2 2251.06   425.4 2252.91   435.2 2256.28   441.7 2261.49
#Mann= 5 ,-1 , 0
       0     .12       0  131.32    .016       0  162.25     .12       0
   230.5    .045       0   243.5     .12       0
Bank Sta=230.5,243.5
XS Rating Curve= 0 ,0
Exp/Cntr=0.3,0.1

Type RM Length L Ch R = 1 ,8842.8  ,295.3,311.1,325.7
XS GIS Cut Line= 3
      1951776.37      212687.235     1951654.842      212598.693
      1951392.69      212548.346
#Sta/Elev= 30
       0 2223.37    26.2 2211.31      36 2209.36    55.6 2203.35   104.6 2194.03
  115.712193.098   130.8  2190.3   137.3 2190.31   143.8 2191.51  150.552190.474
   160.1 2187.88   173.2 2181.56   176.4  2180.9   186.2 2180.86  193.872176.886
   195.9 2176.29  214.012176.844   228.5 2178.31   257.8 2178.81   270.8  2181.4
   280.6 2186.54   287.1 2188.49   326.2 2190.49   335.9 2191.92   345.7 2195.86
   365.2 2205.07   378.2 2211.95   384.8    2214     401 2222.16   417.3 2227.95
#Mann= 5 ,-1 , 0
       0     .12       0  115.71    .016       0  150.55     .12       0
  193.87    .045       0  214.01     .12       0
#XS Ineff= 2 , 0
                          231.17         2180.95
Permanent Ineff=
       F       F
Bank Sta=193.87,214.01
XS Rating Curve= 0 ,0
Exp/Cntr=0.3,0.1

Type RM Length L Ch R = 1 ,8531.8  ,316,306.5,296.4
XS GIS Cut Line= 2
     1951903.106       212484.11     1951656.579       212202.86
#Sta/Elev= 30
       0 2209.54    39.4 2198.57    52.5 2193.79    95.1 2184.55     105 2184.13
   124.7  2186.2   131.2 2185.53   134.5 2183.42   141.1  2175.7  144.35 2173.09
   147.6 2171.92   154.2 2171.46   157.5 2170.08     164 2164.95   167.3 2163.87
   173.9 2162.95  184.762163.866  188.912165.445   200.1 2169.14   216.5 2170.89
   226.4 2173.36   232.9 2175.77   239.5 2179.38   249.3 2185.64     269 2201.74
   321.5 2240.19   324.8 2241.62   347.8 2246.73   357.6 2246.14     374 2246.61
#Mann= 5 ,-1 , 0
       0     .12       0  144.35    .016       0   167.3    .045       0
  184.76    .016       0  188.91     .12       0
Bank Sta=167.3,184.76
XS Rating Curve= 0 ,0
Exp/Cntr=0.3,0.1

Type RM Length L Ch R = 1 ,8225.3  ,241.1,254.6,267.2
XS GIS Cut Line= 4
     1952132.273      212300.082     1952092.342      212197.652
     1951934.356      212126.471     1951824.981       212015.36
#Sta/Elev= 30
       0 2194.33    12.9 2189.22    25.9 2186.77    48.5 2178.85      55 2175.81
    77.6 2162.48    90.5 2158.46  102.472157.704     123 2156.24  146.692157.156
   175.3 2155.24   194.9 2153.01   201.5  2152.7   211.3 2153.06   214.6 2154.05
   217.8  2156.6   227.6 2167.73   240.7 2176.35   247.3 2178.16   260.3 2179.53
   283.2 2178.41   289.7 2181.73   302.7 2192.03   315.7 2200.37   335.2 2210.78
   341.7 2213.44   348.2 2215.02   380.7    2220   416.4  2228.4   439.1 2231.98
#Mann= 5 ,-1 , 0
       0     .12       0  102.47    .016       0  146.69     .12       0
   194.9    .045       0   211.3     .12       0
#XS Ineff= 2 , 0
          173.89 2161.11
Permanent Ineff=
       F       F
Bank Sta=194.9,211.3
XS Rating Curve= 0 ,0
Exp/Cntr=0.3,0.1

Type RM Length L Ch R = 1 ,7970.7  ,371.7,353.2,334
XS GIS Cut Line= 4
     1952318.037      212126.471     1952203.454      212020.568
     1952121.856      211893.832     1951951.717       211890.36
#Sta/Elev= 30
       0 2177.08     9.8 2171.13    29.3 2161.85    35.8 2157.52      39  2155.9
    58.5 2151.89      78 2151.94   86.732151.241   128.82149.701   146.3 2149.39
   175.7 2147.68   195.4 2147.86     212 2145.28   218.3  2144.7     227 2145.26
   241.2 2149.73     251 2152.04   264.2 2152.73   290.4  2151.8   296.9 2152.58
     310 2155.59   319.8 2158.69   329.7 2160.66   349.3  2166.3   368.9 2173.79
   391.8 2183.38   398.4 2186.55     418 2192.76   450.8  2202.1   476.9 2207.55
#Mann= 5 ,-1 , 0
       0     .12       0   86.73    .016       0   128.8     .12       0
     212    .045       0     227     .12       0
#XS Ineff= 2 , 0
          196.08 2151.35
Permanent Ineff=
       F       F
Bank Sta=212,227
XS Rating Curve= 0 ,0
Exp/Cntr=0.3,0.1

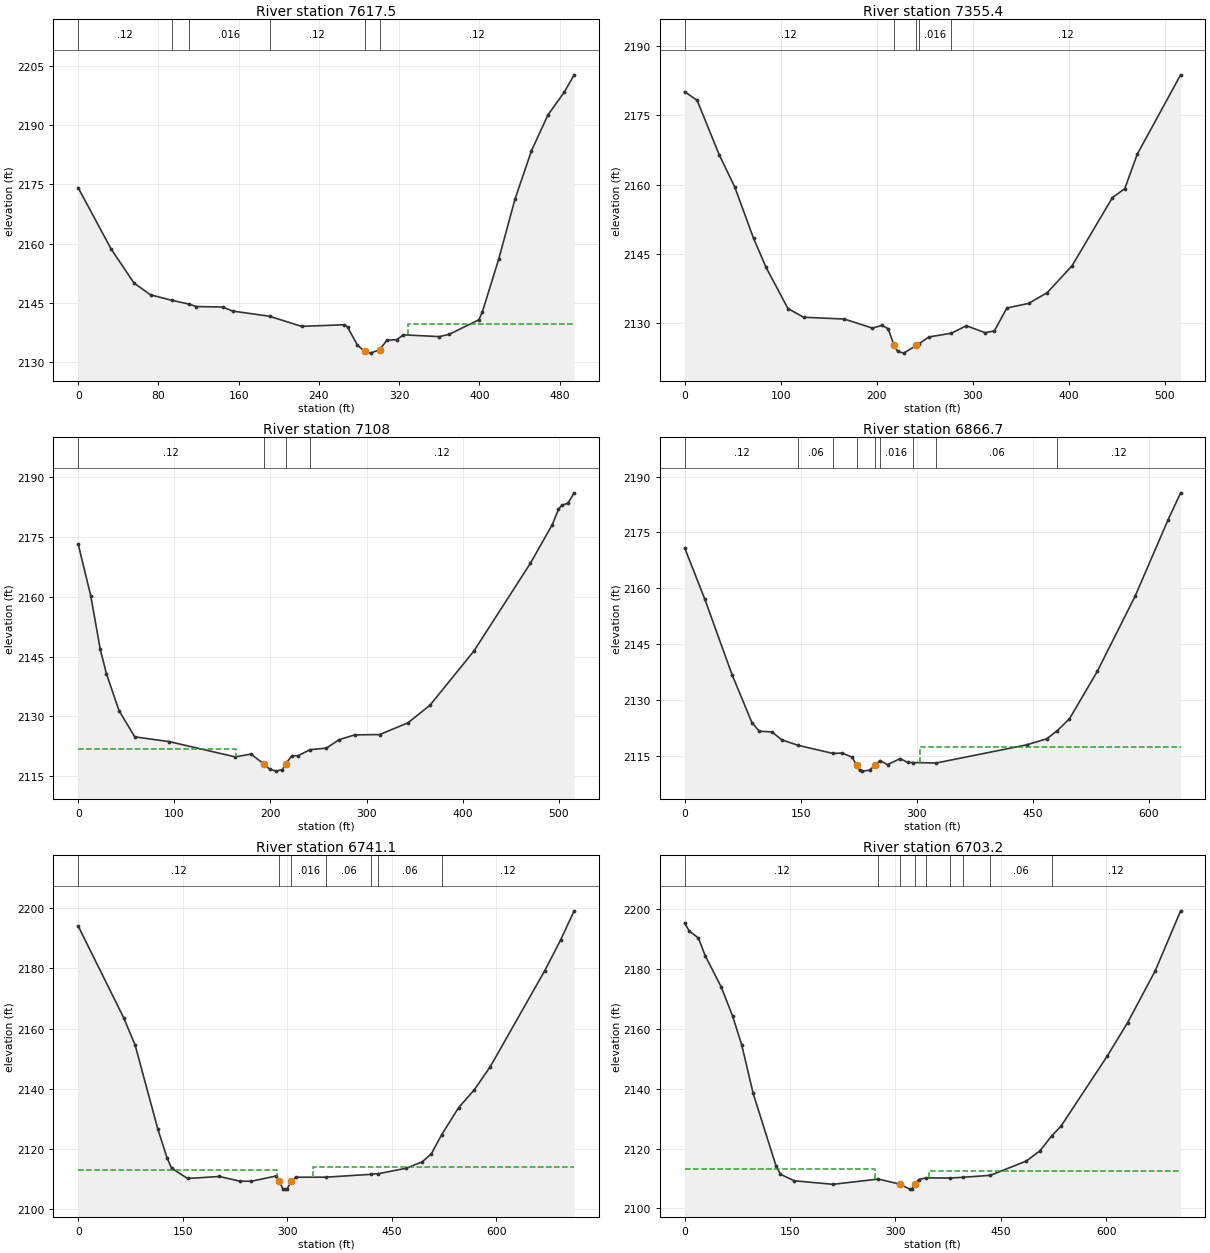
Type RM Length L Ch R = 1 ,7617.5  ,259.8,262.1,264.4
XS GIS Cut Line= 2
     1952493.384      211728.902     1952007.763      211635.112
#Sta/Elev= 30
       0 2174.13    32.8 2158.63    55.7 2149.96    72.1 2146.99   93.722145.586
  110.372144.639   117.9 2144.02   144.1 2143.89     154 2142.87  190.822141.557
   222.7 2138.99   265.3  2139.4   268.6 2138.83   278.4 2134.25   285.7 2132.63
   291.5  2132.2   300.7 2133.08   307.9 2135.48   317.7 2135.61   324.3 2136.84
   360.3 2136.39   370.1 2136.98   399.6 2140.67   402.9 2142.55   419.3 2155.99
   435.6 2171.26     452 2183.52   468.4  2192.6   484.8 2198.44   494.6  2202.8
#Mann= 6 ,-1 , 0
       0     .12       0   93.72     .06       0  110.37    .016       0
  190.82     .12       0   285.7    .045       0   300.7     .12       0
#XS Ineff= 2 , 0
                          329.21         2139.59
Permanent Ineff=
       F       F
Bank Sta=285.7,300.7
XS Rating Curve= 0 ,0
Exp/Cntr=0.3,0.1

Type RM Length L Ch R = 1 ,7355.4  ,258.5,247.4,236.3
XS GIS Cut Line= 3
      1952526.37      211497.999     1952232.967      211409.457
     1952024.634      211437.235
#Sta/Elev= 30
       0 2180.14      13 2178.25    35.9 2166.51    52.2 2159.48    71.7 2148.41
    84.8 2142.09   107.6 2133.16   123.9 2131.29   166.3  2130.9   195.6 2128.94
   205.4 2129.53   211.9 2128.81  218.032125.286   221.7 2123.93   228.2 2123.52
   241.3 2125.19  244.492125.599   254.3 2127.02  277.832127.832   293.4 2129.45
   312.9 2127.95   322.6 2128.33   335.6  2133.3   358.2 2134.28   377.6 2136.61
   403.5 2142.43   445.5 2157.18   458.4 2159.14   471.4 2166.59   516.6 2183.79
#Mann= 5 ,-1 , 0
       0     .12       0  218.03    .045       0   241.3     .12       0
  244.49    .016       0  277.83     .12       0
Bank Sta=218.03,241.3
XS Rating Curve= 0 ,0
Exp/Cntr=0.3,0.1

Type RM Length L Ch R = 1 ,7108    ,243.1,241.3,239.4
XS GIS Cut Line= 3
      1952486.44      211149.041     1952175.676      211211.541
     1951989.912      211282.721
#Sta/Elev= 30
       0 2173.23    13.1 2160.22    22.9 2146.89    29.4  2140.7    42.5 2131.45
    58.8 2124.89    94.8 2123.69   163.4 2119.86   179.7 2120.57   192.8 2118.16
   199.3 2116.74   205.9 2116.29   212.4 2116.68   215.7  2118.1   222.2 2120.15
   228.8 2120.16  241.072121.673   258.2 2122.06   271.2 2124.17   287.6 2125.38
   313.7 2125.47   343.1 2128.43   365.9 2132.82   411.6 2146.42   470.3 2168.42
   493.1 2178.11   499.6 2181.98   502.9 2182.98   509.4 2183.52   515.9 2186.12
#Mann= 4 ,-1 , 0
       0     .12       0   192.8    .045       0   215.7    .016       0
  241.07     .12       0
#XS Ineff= 2 , 0
           164.6  2121.9
Permanent Ineff=
       F       F
Bank Sta=192.8,215.7
XS Rating Curve= 0 ,0
Exp/Cntr=0.3,0.1

Type RM Length L Ch R = 1 ,6866.7  ,141.7,125.6,107
XS GIS Cut Line= 3
     1952491.648      211010.152     1952352.759      210928.555
     1951890.954      211060.499
#Sta/Elev= 30
       0 2170.85    25.8 2157.24    61.2 2136.91      87    2124    96.6 2121.69
   112.8 2121.53   125.6 2119.39  147.122117.894  191.992115.733   203.6 2115.85
   216.6 2114.76   222.32112.595   226.4 2111.18   229.7    2111   239.5 2111.27
     246 2112.67   252.72113.816   262.4 2112.73   278.7 2114.36   288.5 2113.32
  294.872113.298  325.592113.189   442.1 2118.04   468.2 2119.66  481.532121.792
   497.6 2125.02   533.6 2137.75   582.6 2157.94     625 2178.33   641.4 2185.63
#Mann= 9 ,-1 , 0
       0     .12       0  147.12     .06       0  191.99     .12       0
   222.3    .045       0     246     .12       0   252.7    .016       0
  294.87     .12       0  325.59     .06       0  481.53     .12       0
#XS Ineff= 2 , 0
                          304.13         2117.57
Permanent Ineff=
       F       F
Bank Sta=222.3,246
XS Rating Curve= 0 ,0
Exp/Cntr=0.3,0.1

Type RM Length L Ch R = 1 ,6741.1  ,40,37.9,37.9
XS GIS Cut Line= 4
     1952485.408      210757.086     1952218.915      210836.079
     1952195.478       210880.35     1951830.895       211001.01
#Sta/Elev= 30
       0 2194.08    65.4 2163.55    81.8 2154.46   114.4 2126.56   127.5 2117.08
   134.1 2113.61     157  2110.2   202.7 2110.86   232.2  2109.3   248.5 2109.28
   284.2 2111.03  288.632109.245   293.6 2106.86   296.7 2106.66   299.9 2106.76
   306.2 2109.26   312.4 2110.62  356.072110.636  420.342111.586  430.662111.782
   471.2 2113.61     494 2115.76     507 2118.37  521.71 2124.69   546.1 2133.72
   568.9 2139.71   591.7 2147.39   669.8 2179.22   692.6 2189.45   712.1 2199.15
#Mann= 7 ,-1 , 0
       0     .12       0  288.63    .045       0   306.2    .016       0
  356.07     .06       0  420.34     .12       0  430.66     .06       0
  521.71     .12       0
#XS Ineff= 2 , 0
          284.92 2113.01   337.8         2114.16
Permanent Ineff=
       F       F
Bank Sta=288.63,306.2
XS Rating Curve= 0 ,0
Exp/Cntr=0.3,0.1

Type RM Length L Ch R = 1 ,6703.2  ,19.5,36.9,53.6
XS GIS Cut Line= 4
     1952468.915      210732.781     1952185.929       210817.85
     1952162.492      210862.121     1951820.478      210975.836
#Sta/Elev= 30
       0 2195.41     6.5 2192.76    19.5 2190.44    29.2 2184.52      52 2174.04
    68.2 2164.34    81.2 2154.67    97.4 2138.52   129.9 2114.29   136.4 2111.38
   155.9 2109.21   211.1 2108.02  275.562109.777  306.13 2108.09   320.5 2106.41
   323.7 2106.53   328.2 2108.09   333.1 2109.63  343.932110.168  378.322110.131
  396.542110.375  435.262111.032   486.5 2115.83   506.1  2119.3   522.72124.287
   535.6 2127.43   601.2  2150.8   630.6 2162.14     670 2179.54     706 2199.52
#Mann= 9 ,-1 , 0
       0     .12       0  275.56    .016       0  306.13    .045       0
   328.2    .016       0  343.93     .12       0  378.32     .06       0
  396.54     .12       0  435.26     .06       0   522.7     .12       0
#XS Ineff= 2 , 0
          271.62 2113.18  347.57         2112.33
Permanent Ineff=
       F       F
Bank Sta=306.13,328.2
XS Rating Curve= 0 ,0
Exp/Cntr=0.3,0.1

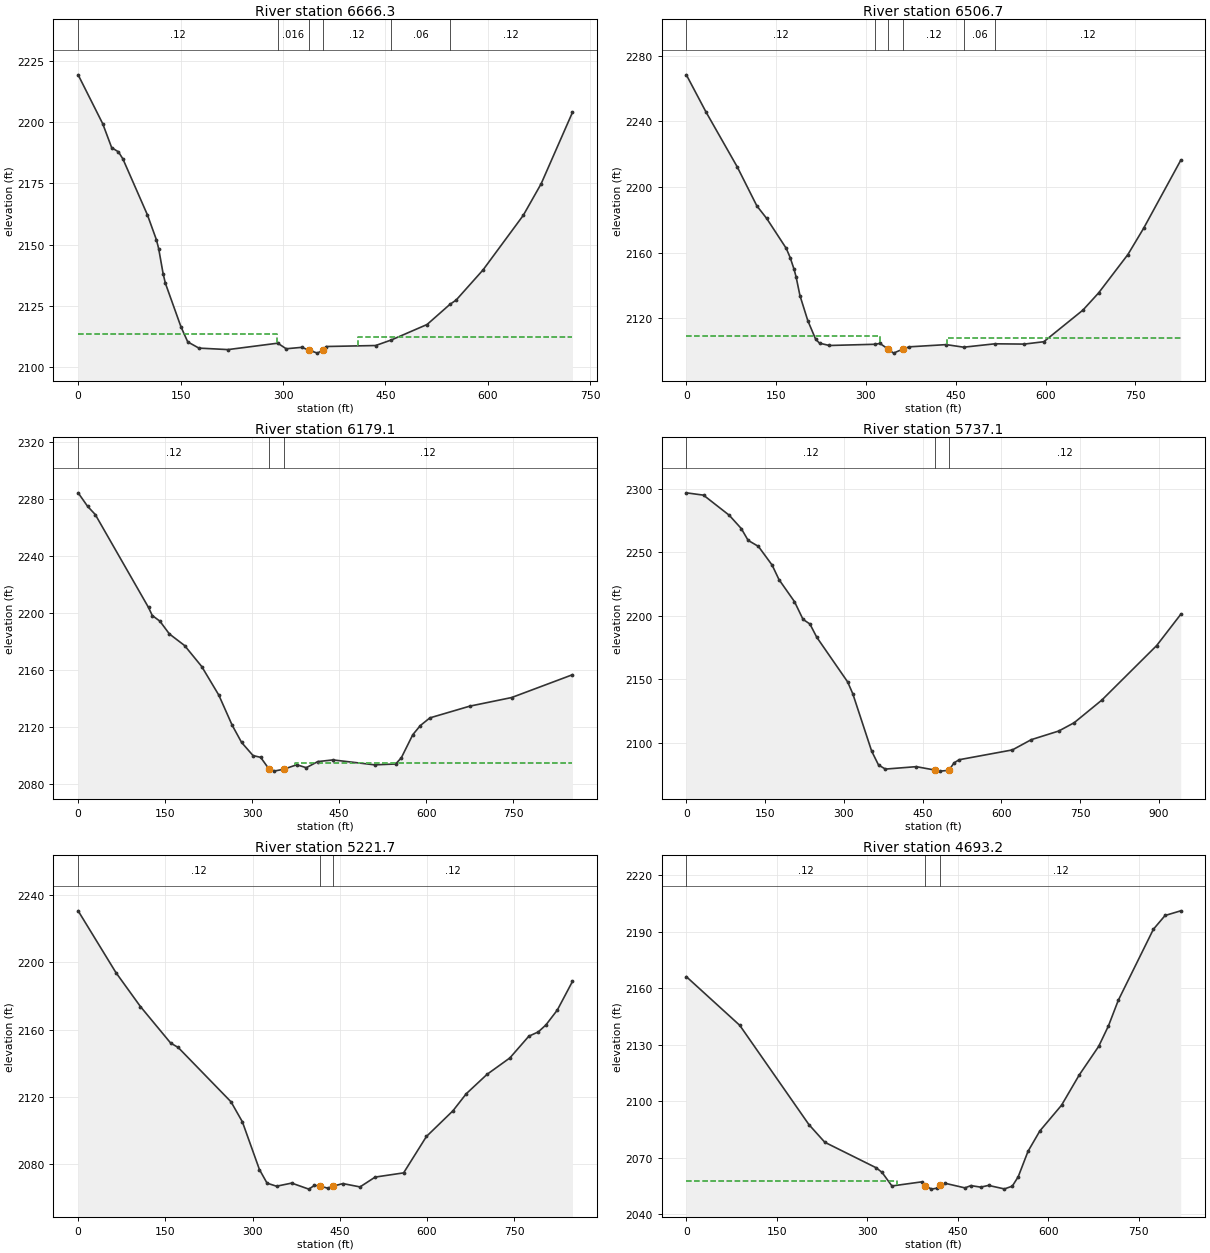
Type RM Length L Ch R = 1 ,6666.3  ,150.3,159.6,168.5
XS GIS Cut Line= 2
     1952477.596      210693.284     1951797.908      210941.982
#Sta/Elev= 30
       0 2219.27      36 2199.34    49.1 2189.59      59 2187.87    65.5 2185.01
   101.5 2162.15   114.6 2152.04   117.9 2148.47   124.4 2138.25   127.7 2134.35
   150.6 2116.52   160.5 2110.39   176.8 2107.87   219.4 2107.26  292.292109.875
   304.6  2107.6   327.5 2108.18   337.3  2107.1   350.4 2105.82  357.932107.064
   363.5 2108.52   435.6 2108.92  458.642111.194   510.9 2117.49  544.262125.676
   553.5 2127.46   592.8 2139.73   651.7 2161.97   677.9 2174.85   723.8 2203.98
#Mann= 6 ,-1 , 0
       0     .12       0  292.29    .016       0   337.3    .045       0
  357.93     .12       0  458.64     .06       0  544.26     .12       0
#XS Ineff= 2 , 0
          291.43 2113.78  410.06         2112.23
Permanent Ineff=
       F       F
Bank Sta=337.3,357.93
XS Rating Curve= 0 ,0
Exp/Cntr=0.3,0.1

Type RM Length L Ch R = 1 ,6506.7  ,334.2,327.6,320.2
XS GIS Cut Line= 4
     1952489.912      210581.332     1952285.051      210659.457
     1951949.981      210645.568     1951712.134      210775.777
#Sta/Elev= 30
       0 2268.31    32.7 2245.77    85.1  2212.2   117.8 2188.51   134.2 2180.88
   166.9 2162.64   173.4 2157.08     180 2149.86   183.3 2145.34   189.8 2133.88
   202.9 2118.64     216 2107.34   222.5 2104.94   238.8 2103.53  315.692104.275
   323.4  2104.8  337.452101.232   346.2 2098.88   362.5 2101.49   372.3 2102.71
   434.1 2104.06  463.362102.491  515.442104.558   564.4 2104.38   597.1 2105.82
   662.4 2125.05   688.6  2135.5   737.6 2158.91   763.7 2174.78   825.8 2216.25
#Mann= 6 ,-1 , 0
       0     .12       0  315.69    .016       0  337.45    .045       0
   362.5     .12       0  463.36     .06       0  515.44     .12       0
#XS Ineff= 2 , 0
          324.05 2109.05  434.63         2108.23
Permanent Ineff=
       F       F
Bank Sta=337.45,362.5
XS Rating Curve= 0 ,0
Exp/Cntr=0.3,0.1

Type RM Length L Ch R = 1 ,6179.1  ,434.1,442,444.2
XS GIS Cut Line= 2
     1952420.467      210244.527     1951599.287      210471.957
#Sta/Elev= 30
       0 2284.36    16.4 2274.85    29.5 2269.16   121.3 2203.96   127.8 2198.33
   140.9 2194.38   157.3  2185.4   183.5 2177.27     213 2162.57   242.5  2142.5
   265.5  2121.4   281.8 2109.29   301.5  2100.1   314.6 2098.86  329.432090.448
   337.6  2089.2     354 2090.51   376.9 2093.65   393.3 2091.61   412.9 2095.87
   439.2 2097.07   511.3  2093.6   547.3 2094.21   557.1 2098.58   576.8 2114.72
   589.9 2121.18   606.3 2126.54   675.1 2134.77   747.2  2140.8   852.1  2156.8
#Mann= 3 ,-1 , 0
       0     .12       0  329.43    .045       0     354     .12       0
#XS Ineff= 2 , 0
                          374.35         2094.99
Permanent Ineff=
       F       F
Bank Sta=329.43,354
XS Rating Curve= 0 ,0
Exp/Cntr=0.3,0.1

Type RM Length L Ch R = 1 ,5737.1  ,515.9,515.4,518.4
XS GIS Cut Line= 3
     1952470.258      209933.088     1951976.977      209914.918
     1951539.571      210012.368
#Sta/Elev= 30
       0 2296.83    32.7    2295    81.7 2279.17   104.6  2268.7   117.7 2259.39
   137.3 2254.62   163.4 2239.89   176.5 2228.48     206 2211.11   222.3 2197.14
   235.4 2193.49   248.4 2183.09   307.3 2147.86   317.1 2138.53     353 2093.39
   366.1 2082.43   379.2 2079.19     438  2081.1     474 2078.39   483.8 2077.58
   500.2 2078.23     510  2084.1   519.8 2086.57   621.2  2094.3   657.2 2102.38
   709.5 2109.18   738.9 2115.73   791.3 2133.46     896  2176.5   941.8 2201.05
#Mann= 3 ,-1 , 0
       0     .12       0     474    .045       0   500.2     .12       0
Bank Sta=474,500.2
XS Rating Curve= 0 ,0
Exp/Cntr=0.3,0.1

Type RM Length L Ch R = 1 ,5221.7  ,526.7,528.5,529.2
XS GIS Cut Line= 3
     1952401.544      209539.145     1952133.315      209450.603
     1951565.606      209450.603
#Sta/Elev= 30
       0 2230.43    64.9 2193.84   107.1 2173.66   159.1 2151.99   172.1 2149.36
     263 2117.09   282.5 2105.23   311.8 2076.95   324.9 2068.87   341.2 2067.05
   367.3  2068.9   396.7 2065.32   406.4 2067.52   416.2  2067.2   429.3 2065.85
   439.1 2067.14   455.4 2068.61   484.8 2066.63   510.8 2072.46   559.8 2074.97
     599 2096.55   644.6 2111.79   667.5 2121.91   703.4 2133.45   742.5 2143.15
   775.1 2156.04   791.4  2158.6   804.5 2162.73   824.1 2171.55   850.2 2188.56
#Mann= 3 ,-1 , 0
       0     .12       0   416.2    .045       0   439.1     .12       0
Bank Sta=416.2,439.1
XS Rating Curve= 0 ,0
Exp/Cntr=0.3,0.1

Type RM Length L Ch R = 1 ,4693.2  ,416.6,427.1,435.9
XS GIS Cut Line= 4
     1952448.419      209072.999      1952193.21      208945.395
     1951846.856       208929.77     1951669.773       208867.27
#Sta/Elev= 30
       0 2166.13    88.6 2140.26   203.3  2087.5   229.6 2078.13   314.8 2064.57
   324.6 2062.09   340.9  2054.9     390 2057.07   396.5 2055.14   406.4 2053.22
   416.2 2053.77  421.282055.288   429.2 2056.32     462 2053.88   471.8 2055.09
   488.1 2054.28   501.2  2055.2   527.4 2053.32   540.5 2054.81   550.3 2059.76
   566.6 2073.32   586.2 2084.13   622.2 2097.82   651.5 2113.87   683.8  2129.1
     700 2139.98   716.2  2153.5   774.5 2191.32   793.9 2198.64   819.8 2201.12
#Mann= 3 ,-1 , 0
       0     .12       0   396.5    .045       0  421.28     .12       0
#XS Ineff= 2 , 0
          349.02 2057.66
Permanent Ineff=
       F       F
Bank Sta=396.5,421.28
XS Rating Curve= 0 ,0
Exp/Cntr=0.3,0.1