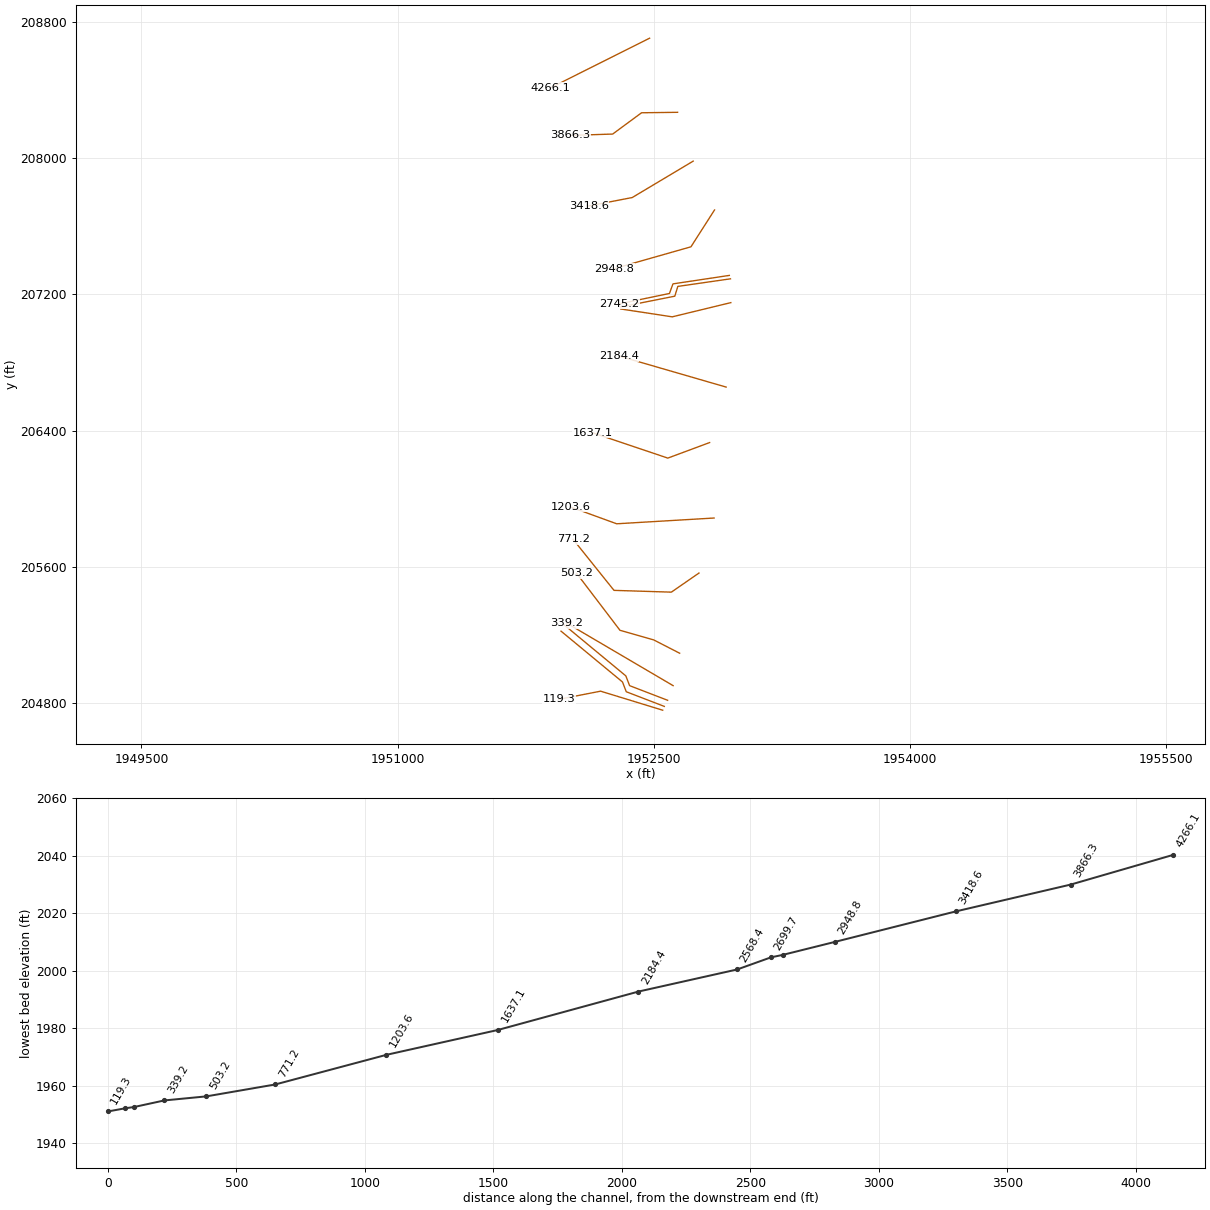
HEC-RAS study NFKMTNCK.prj: NFKMTNCK

--- NFKMTNCK.g01 (geometry) --- (continued)

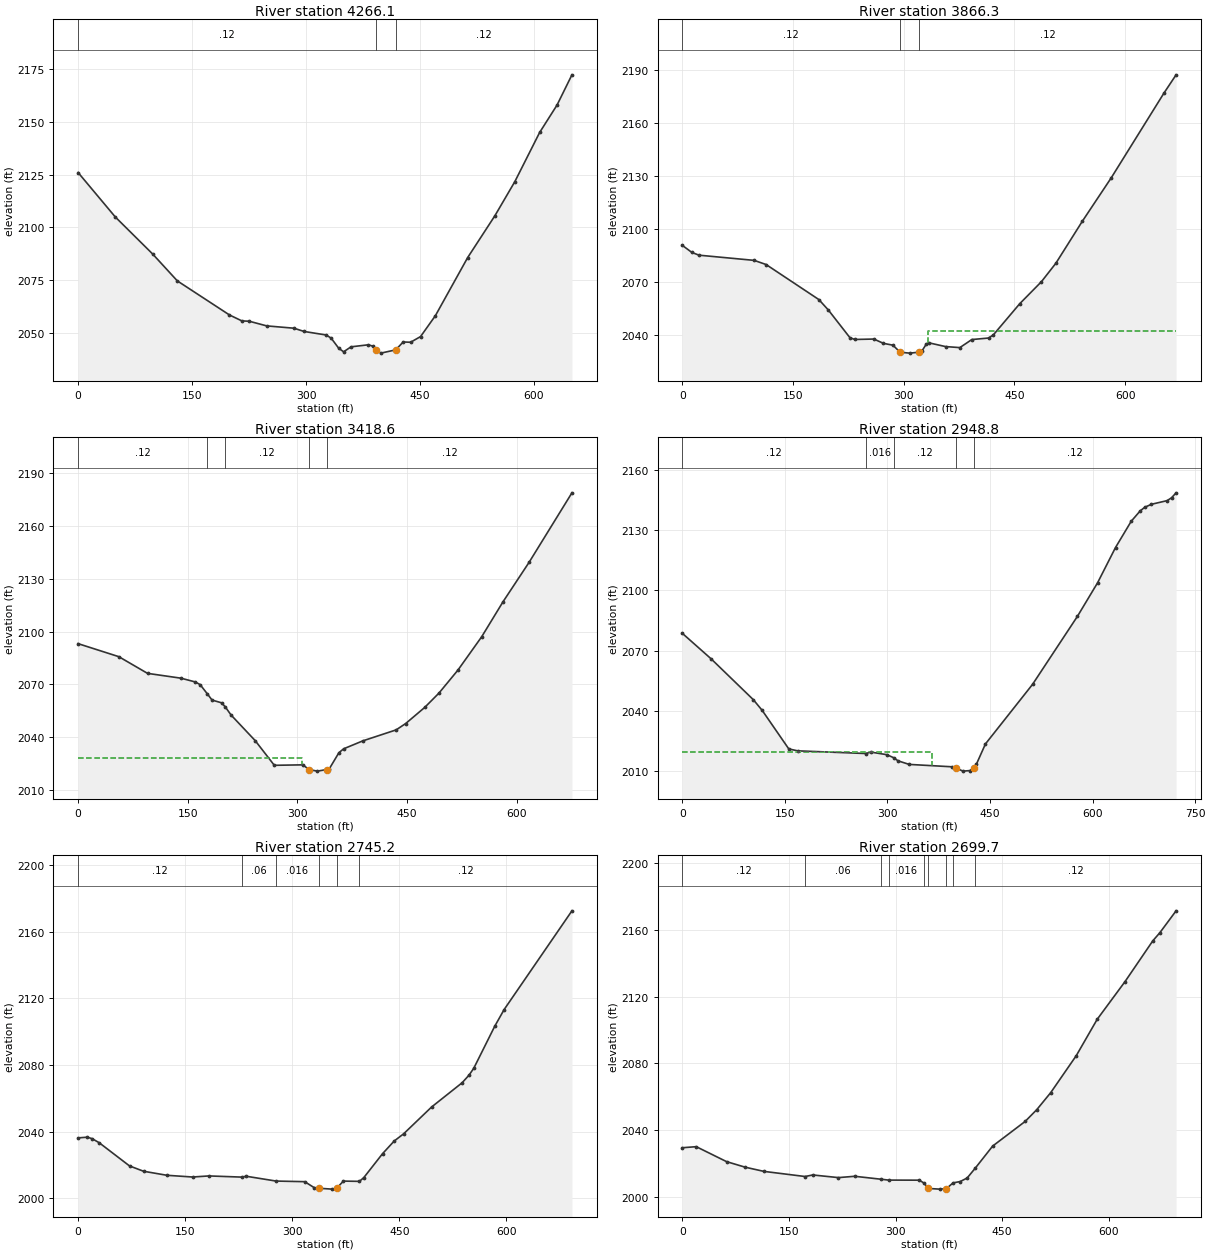
Type RM Length L Ch R = 1 ,4266.1  ,395.9,399.8,403.5
XS GIS Cut Line= 2
      1952474.46      208703.207     1951893.731      208411.541
#Sta/Elev= 30
       0 2126.04      49 2104.94      98 2087.44   130.6 2074.64   199.2 2058.48
   215.5 2055.67   225.3  2055.5   248.2  2053.3   284.1  2052.2   297.2 2050.67
   326.6 2048.97   333.1 2047.45   342.9 2042.73   349.4 2041.01   359.2 2043.37
   382.1 2044.34   388.6 2043.59  392.53 2041.85   398.4 2040.38     418 2041.93
   427.8 2045.67   437.6 2045.54   450.7 2048.24   470.2 2058.14   512.7 2085.72
   548.6  2105.6   574.8 2121.76   607.4 2145.05   630.3 2158.06   649.9 2172.39
#Mann= 3 ,-1 , 0
       0     .12       0  392.53    .045       0     418     .12       0
Bank Sta=392.53,418
XS Rating Curve= 0 ,0
Exp/Cntr=0.3,0.1

Type RM Length L Ch R = 1 ,3866.3  ,449.2,447.7,445
XS GIS Cut Line= 4
     1952638.523      208268.312     1952427.585      208265.707
     1952258.315      208140.707     1952010.919      208132.895
#Sta/Elev= 30
       0  2090.9      13 2086.89    22.7 2085.33    97.4  2082.4   113.6 2080.05
     185 2060.28     198 2054.32   227.1 2038.76   233.6 2037.74   259.5 2037.98
   272.5 2035.55   285.4 2034.51   295.1 2030.54   308.1 2030.03     321 2030.56
   324.3 2031.02   330.7 2035.21     334 2035.85   356.6 2033.73     376 2033.15
   392.2 2037.69   414.9 2038.56   421.4 2040.34   457.2 2057.97   486.5 2070.36
     506 2080.74   541.9 2104.48     581 2128.97   652.6 2176.94   668.9 2187.16
#Mann= 3 ,-1 , 0
       0     .12       0   295.1    .045       0     321     .12       0
#XS Ineff= 2 , 0
                           332.3          2042.8
Permanent Ineff=
       F       F
Bank Sta=295.1,321
XS Rating Curve= 0 ,0
Exp/Cntr=0.3,0.1

Type RM Length L Ch R = 1 ,3418.6  ,474.9,469.8,463.9
XS GIS Cut Line= 3
     1952729.669      207981.853     1952372.898      207768.312
      1952117.69      207718.832
#Sta/Elev= 30
       0 2093.12    55.7 2085.73      95 2076.24   140.8  2073.5   160.4 2071.36
     167 2069.84  176.582064.741   183.3 2061.07   196.4  2059.5  201.322057.223
   209.5 2052.49   242.3 2038.04   268.5    2024   307.8 2024.26  315.852021.563
   327.4 2020.69   340.5 2021.59   343.8 2022.05   356.9 2031.16   363.4 2033.38
   389.6 2037.88   435.3 2044.14   448.3 2047.74   474.3 2056.88   493.8 2065.02
   519.8 2078.11   552.3 2097.05   581.5 2116.94   617.3 2139.43   675.8 2178.83
#Mann= 5 ,-1 , 0
       0     .12       0  176.58    .016       0  201.32     .12       0
  315.85    .045       0   340.5     .12       0
#XS Ineff= 2 , 0
           306.3 2028.11
Permanent Ineff=
       F       F
Bank Sta=315.85,340.5
XS Rating Curve= 0 ,0
Exp/Cntr=0.3,0.1

Type RM Length L Ch R = 1 ,2948.8  ,189.7,203.6,228
XS GIS Cut Line= 3
     1952854.669      207695.395     1952716.648      207479.249
     1952268.731      207351.645
#Sta/Elev= 30
       0 2078.63    42.2 2065.92   103.9 2045.62   116.9  2040.3   155.8 2021.14
   168.8 2020.18  268.112018.857   276.1 2019.54   299.1 2018.28  309.562016.716
   315.5 2015.22   331.9 2013.44   394.2 2012.26   400.8 2011.56   410.6  2010.1
   420.4 2010.36  426.232011.432   430.3 2013.64   443.4 2023.62   512.3 2053.23
   577.9 2087.03   607.4 2103.72   633.6 2121.24   656.6  2134.3   669.7 2139.45
   676.3 2141.23   686.1 2142.73   709.1 2144.55   715.6 2145.98   722.2 2148.43
#Mann= 5 ,-1 , 0
       0     .12       0  268.11    .016       0  309.56     .12       0
   400.8    .045       0  426.23     .12       0
#XS Ineff= 2 , 0
          364.91 2019.73
Permanent Ineff=
       F       F
Bank Sta=400.8,426.23
XS Rating Curve= 0 ,0
Exp/Cntr=0.3,0.1

Type RM Length L Ch R = 1 ,2745.2  ,31.7,45.5,33.2
XS GIS Cut Line= 4
     1952941.331      207311.466     1952611.313      207261.794
      1952590.78      207205.481      1952298.97        207144.8
#Sta/Elev= 30
       0 2036.33    13.1 2036.75    19.6 2035.85    29.4 2033.46      72  2019.5
    91.6 2016.31   124.3 2013.88   160.3 2012.84   183.2 2013.49   229.22012.787
   235.6 2013.29  277.252010.411   317.4 2010.04   330.5  2006.5   336.9  2006.1
   355.8 2005.57   362.1  2006.1   371.6 2010.39  394.062010.233   400.2  2012.5
   426.4 2026.83   442.8 2034.47   455.9 2038.75   495.2 2054.89   537.8 2069.38
   547.6    2074   554.2 2078.11   583.6 2103.36   596.7 2113.34   691.7 2172.61
#Mann= 6 ,-1 , 0
       0     .12       0   229.2     .06       0  277.25    .016       0
   336.9    .045       0   362.1    .016       0  394.06     .12       0
Bank Sta=336.9,362.1
XS Rating Curve= 0 ,0
Exp/Cntr=0.3,0.1

Type RM Length L Ch R = 1 ,2699.7  ,159.1,131.4,117.8
XS GIS Cut Line= 4
     1952948.044        207291.5     1952639.793       207246.89
     1952622.141      207189.608     1952305.046      207126.571
#Sta/Elev= 30
       0  2029.5    19.7 2030.14    62.3 2021.19    88.5 2017.86   114.8 2015.35
  172.762012.277   183.6  2013.2   219.7 2011.62   242.6 2012.41  280.272010.619
   290.32010.125   333.6 2010.08  340.022008.329   346.2 2005.13   361.9 2004.72
   371.4 2004.99  381.042008.467     391 2009.26   400.8 2011.39  412.112017.239
   436.7 2030.52   482.4 2045.27   498.8 2052.35   518.4 2062.54   554.3 2084.66
   583.7 2106.41   622.9 2129.02     662 2153.44   671.8 2158.24   694.7 2171.38
#Mann= 9 ,-1 , 0
       0     .12       0  172.76     .06       0  280.27     .12       0
   290.3    .016       0  340.02     .12       0   346.2    .045       0
   371.4     .12       0  381.04    .016       0  412.11     .12       0
Bank Sta=346.2,371.4
XS Rating Curve= 0 ,0
Exp/Cntr=0.3,0.1

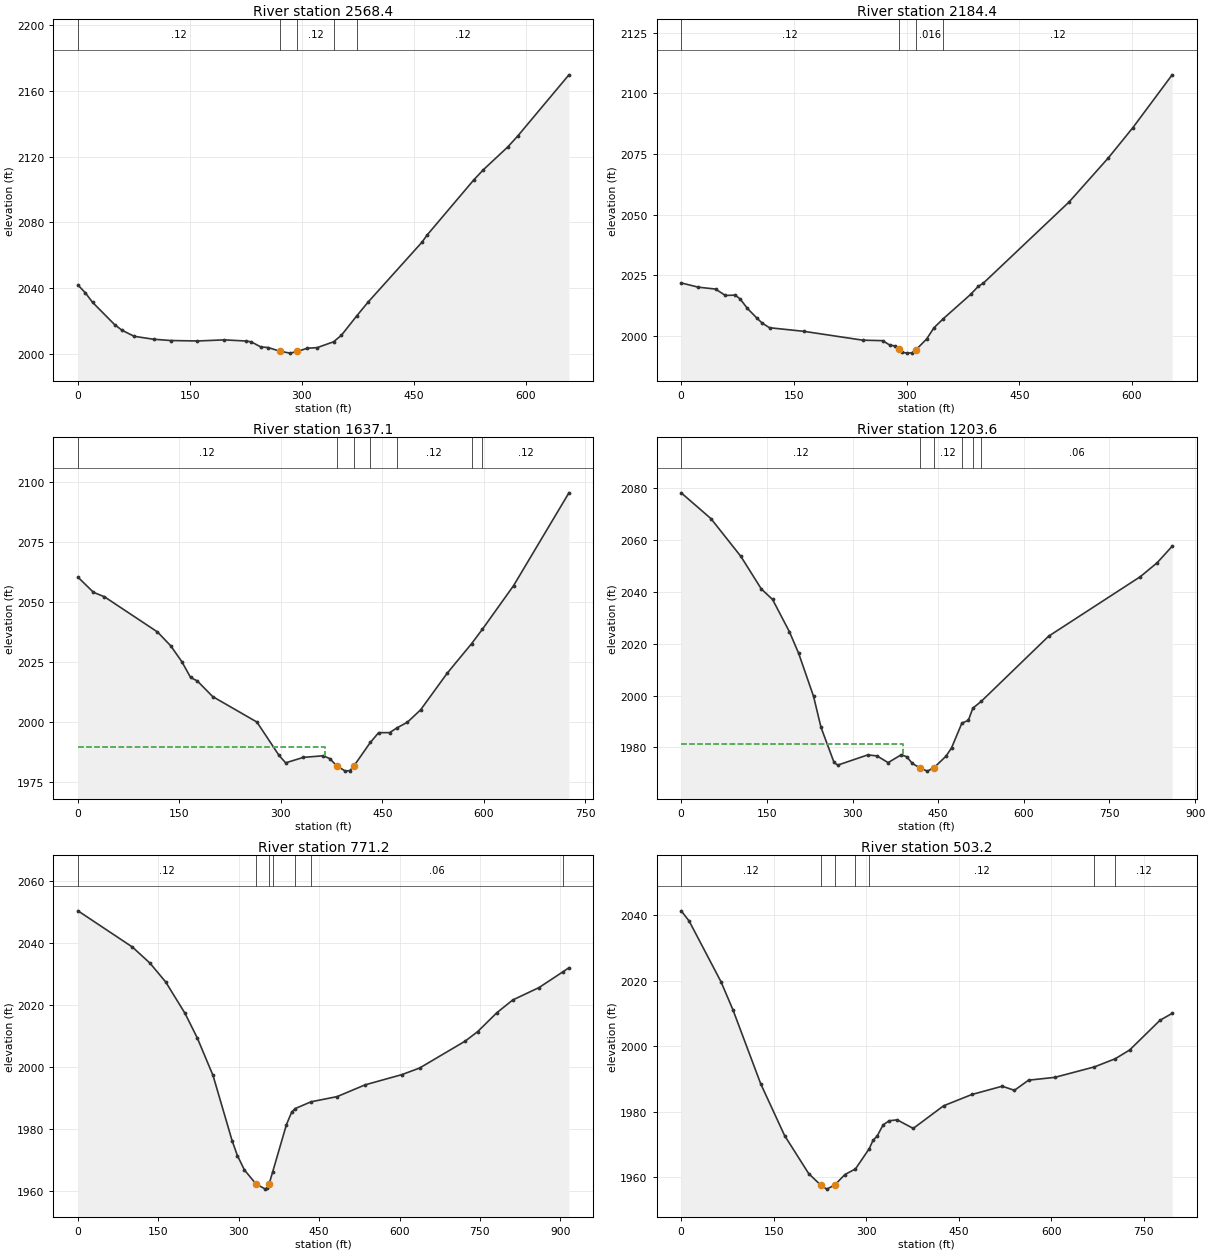
Type RM Length L Ch R = 1 ,2568.4  ,395.3,384,371.6
XS GIS Cut Line= 3
     1952950.012      207151.744      1952607.13      207068.411
     1952305.914      207114.418
#Sta/Elev= 30
       0 2041.92     9.8 2037.23    19.6 2031.38      49 2017.89    58.8 2014.48
    75.2 2010.75   101.3 2008.95   124.2 2008.18   160.1  2007.9     196 2008.57
   225.4 2007.87     232 2007.37     245 2004.26   254.8 2003.91   271.2 2001.56
   284.2 2000.51     294 2001.52   307.1  2003.5   320.2 2003.82  342.38 2007.41
   352.9  2011.4  373.652023.307   388.9  2031.7     461 2068.09   467.5 2072.25
   529.8 2105.67   542.9 2112.01   575.7 2125.91   588.8 2132.43   657.6 2169.76
#Mann= 5 ,-1 , 0
       0     .12       0   271.2    .045       0     294     .12       0
  342.38    .016       0  373.65     .12       0
Bank Sta=271.2,294
XS Rating Curve= 0 ,0
Exp/Cntr=0.3,0.1

Type RM Length L Ch R = 1 ,2184.4  ,547.1,547.3,545.5
XS GIS Cut Line= 2
     1952922.377      206656.332     1952294.773      206838.624
#Sta/Elev= 30
       0  2021.8    22.9 2020.04    45.8 2019.26    58.8 2016.63    71.9 2016.77
    78.4 2015.22    88.2 2011.27   101.3 2007.12   107.8 2005.23   117.6 2003.31
   163.4 2001.82   241.8 1998.17     268 1997.98   277.8 1996.13   284.3 1995.82
  290.211994.365   294.1 1993.19   300.6 1992.83   307.2 1992.96   312.8 1994.31
   326.8 1998.69   336.6 2003.34   348.9 2007.04   385.6 2017.16   395.4 2020.39
   401.9 2021.62   516.3  2055.2   568.6 2073.41   601.3 2085.91   653.5 2107.67
#Mann= 4 ,-1 , 0
       0     .12       0  290.21    .045       0   312.8    .016       0
   348.9     .12       0
Bank Sta=290.21,312.8
XS Rating Curve= 0 ,0
Exp/Cntr=0.3,0.1

Type RM Length L Ch R = 1 ,1637.1  ,424.5,433.5,441.9
XS GIS Cut Line= 3
     1952826.023      206330.812     1952581.231      206239.666
     1952141.127      206388.103
#Sta/Elev= 30
       0 2060.39    22.9 2054.08    39.2  2052.2   117.5 2037.54   137.1 2031.76
   153.5 2025.14   166.5 2018.54   176.3 2017.12   199.2 2010.56   264.5 1999.95
   297.2 1986.03     307 1982.93   333.2 1985.21   362.6 1985.87   372.4 1984.67
   382.2 1981.72   395.3 1979.47   401.9 1979.72  407.85 1981.62   432.11991.422
   444.4 1995.51   460.7 1995.54  471.49 1997.51   486.9 1999.86   506.5 2005.05
   545.8 2020.34  581.792032.646  597.852038.684   643.9 2056.87   725.7 2095.58
#Mann= 7 ,-1 , 0
       0     .12       0   382.2    .045       0  407.85     .12       0
   432.1    .016       0  471.49     .12       0  581.79     .06       0
  597.85     .12       0
#XS Ineff= 2 , 0
          364.91 1989.56
Permanent Ineff=
       F       F
Bank Sta=382.2,407.85
XS Rating Curve= 0 ,0
Exp/Cntr=0.3,0.1

Type RM Length L Ch R = 1 ,1203.6  ,434,432.4,428.7
XS GIS Cut Line= 3
     1952852.065      205888.103     1952281.752      205854.249
     1952010.919      205953.207
#Sta/Elev= 30
       0 2078.22    52.2 2068.25   104.5  2053.7   140.4  2041.1     160 2037.07
   189.4 2024.67   205.7 2016.28   231.8 1999.67   244.8 1987.76   267.7 1974.16
   274.2 1973.15   326.5 1977.08   342.8 1976.72   362.4 1974.11   385.2 1977.13
     395 1976.38   404.8 1973.78   417.9 1972.12   430.9 1970.83  442.22 1972.07
   463.6 1976.57   473.4  1979.8  491.541989.365   502.8  1990.4  510.73 1995.11
  525.54 1997.78   643.4  2022.9     804 2045.87   833.4 2051.23   859.7  2057.6
#Mann= 6 ,-1 , 0
       0     .12       0   417.9    .045       0  442.22     .12       0
  491.54    .016       0  510.73     .12       0  525.54     .06       0
#XS Ineff= 2 , 0
          388.03 1981.28
Permanent Ineff=
       F       F
Bank Sta=417.9,442.22
XS Rating Curve= 0 ,0
Exp/Cntr=0.3,0.1

Type RM Length L Ch R = 1 ,771.2   ,273.5,268,262.4
XS GIS Cut Line= 4
     1952763.523      205565.187     1952602.065      205453.207
     1952266.127      205463.624     1952026.544      205763.103
#Sta/Elev= 30
       0 2050.29   101.5 2038.62   134.3 2033.43   163.7 2027.35   199.8 2017.21
   222.6 2009.31     252 1997.19   287.9    1976   297.6  1971.3   310.7 1966.69
  332.621962.116   349.9 1960.53   353.1 1960.82   356.4 1962.04  363.131965.987
     389 1981.34   398.8 1985.39  405.481986.528  434.861988.696   483.6 1990.37
   535.9 1994.17   604.7 1997.48   637.5 1999.59   722.7 2008.29   745.7 2011.32
   781.7 2017.44   811.2 2021.53   860.4 2025.55   905.72030.713   916.1 2031.92
#Mann= 7 ,-1 , 0
       0     .12       0  332.62    .045       0   356.4     .12       0
  363.13    .016       0  405.48     .12       0  434.86     .06       0
   905.7     .12       0
Bank Sta=332.62,356.4
XS Rating Curve= 0 ,0
Exp/Cntr=0.3,0.1

Type RM Length L Ch R = 1 ,503.2   ,169.4,164,157.8
XS GIS Cut Line= 4
     1952650.463      205094.891     1952498.553      205173.016
      1952301.07      205229.439     1952047.164      205563.641
#Sta/Elev= 30
       0 2041.25    12.9 2038.14    64.5 2019.64    83.8 2011.12   128.9 1988.52
   167.6 1972.74   206.7 1961.13   226.2 1957.62     236 1956.39   249.1 1957.68
   265.4 1960.84  282.521962.551  304.851968.715     311 1971.28   317.5 1972.51
   327.3 1975.97   337.1 1977.23   350.1 1977.52   376.2  1974.9   425.4  1981.8
   471.3 1985.25   520.5 1987.77   540.2 1986.52   563.1 1989.61   605.7 1990.47
  669.991993.669  703.531996.135   727.1 1998.83   776.2 2007.88   795.9 2009.98
#Mann= 7 ,-1 , 0
       0     .12       0   226.2    .045       0   249.1     .12       0
  282.52    .016       0  304.85     .12       0  669.99     .06       0
  703.53     .12       0
Bank Sta=226.2,249.1
XS Rating Curve= 0 ,0
Exp/Cntr=0.3,0.1

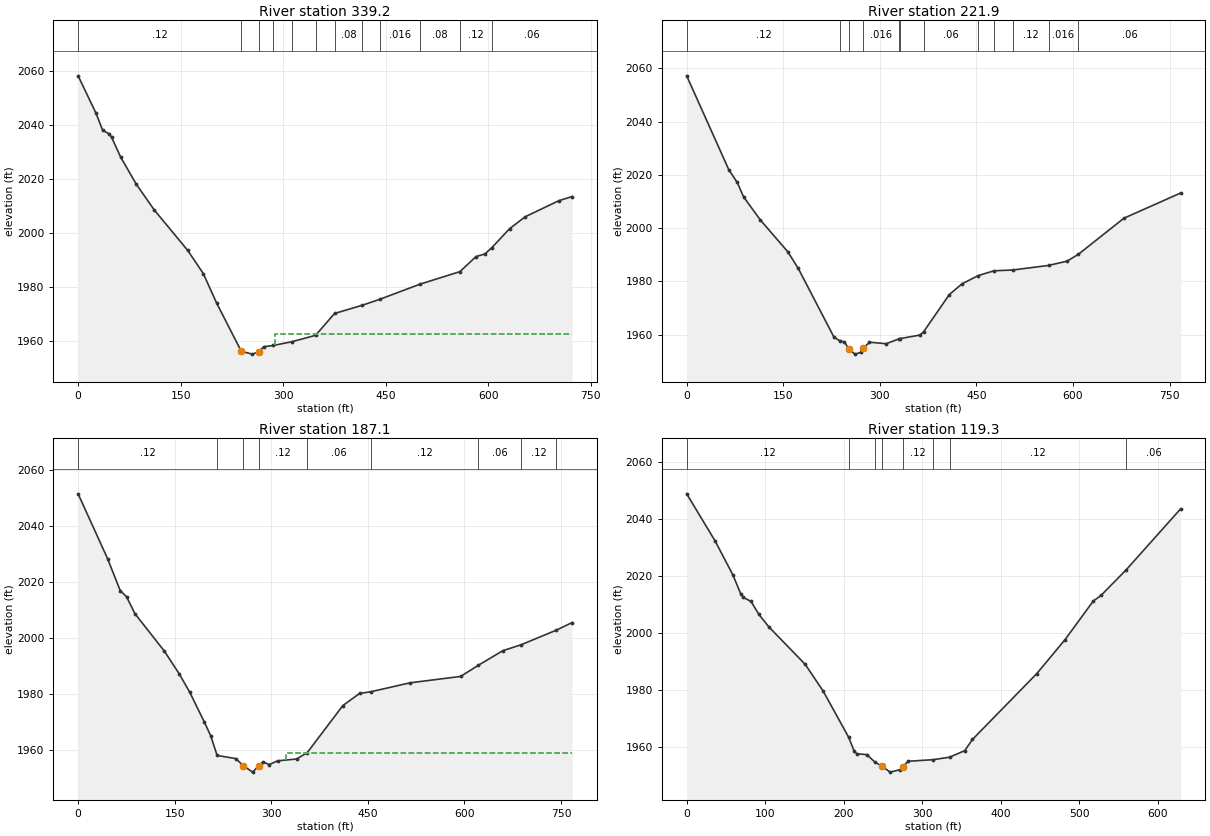
Type RM Length L Ch R = 1 ,339.2   ,130.7,117.3,100.3
XS GIS Cut Line= 2
     1952612.051      204904.787     1951989.221       205271.54
#Sta/Elev= 30
       0 2058.08    26.2 2044.22      36 2037.85    45.8 2036.57    49.1 2035.25
    62.1 2028.03      85 2017.96   111.2 2008.46   160.3 1993.41   183.2  1984.8
   202.8 1973.82   238.8 1955.99   255.1 1954.97   264.9 1955.93   271.5 1957.72
  285.36 1958.17  313.131959.584  347.411961.945  375.221970.034  415.971973.094
  442.061975.348  500.271980.899  558.491985.519   582.2 1991.12   595.2  1992.1
  605.341994.423   631.2 2001.42   654.1 2005.86   703.2  2011.8   722.8 2013.36
#Mann= 12 ,-1 , 0
       0     .12       0   238.8    .045       0   264.9     .12       0
  285.36    .016       0  313.13     .12       0  347.41     .06       0
  375.22     .08       0  415.97     .12       0  442.06    .016       0
  500.27     .08       0  558.49     .12       0  605.34     .06       0
#XS Ineff= 2 , 0
                          287.53         1962.53
Permanent Ineff=
       F       F
Bank Sta=238.8,264.9
XS Rating Curve= 0 ,0
Exp/Cntr=0.3,0.1

Type RM Length L Ch R = 1 ,221.9   ,38,34.9,36.5
XS GIS Cut Line= 4
      1952580.15      204818.741     1952357.494      204904.678
     1952335.359       204961.97     1951975.658      205260.147
#Sta/Elev= 30
       0 2057.18    65.4 2021.93    78.5 2017.16    88.3 2011.76   114.4 2003.06
   156.9 1991.17   173.3 1984.86   228.9    1959  238.451957.622   245.1  1957.3
   251.6 1954.68   261.3 1952.69     271 1953.36   274.2 1954.85   283.9 1957.17
   309.9  1956.6  329.38 1958.38  330.53 1958.49   362.2 1959.85   367.91961.062
   407.9 1975.05   427.5 1979.06  452.791982.176  477.351983.981  506.04 1984.27
  561.951985.987   590.9 1987.61  608.24 1990.15   679.1 2003.72   767.3  2013.2
#Mann= 12 ,-1 , 0
       0     .12       0  238.45    .016       0   251.6    .045       0
   274.2    .016       0  329.38     .12       0  330.53     .08       0
   367.9     .06       0  452.79     .12       0  477.35     .06       0
  506.04     .12       0  561.95    .016       0  608.24     .06       0
Bank Sta=251.6,274.2
XS Rating Curve= 0 ,0
Exp/Cntr=0.3,0.1

Type RM Length L Ch R = 1 ,187.1   ,46,67.8,88.8
XS GIS Cut Line= 4
     1952560.619      204782.933     1952337.963      204868.871
     1952315.827      204926.163     1951956.127       205224.34
#Sta/Elev= 30
       0 2051.35    45.8 2028.24    65.4 2016.88    75.2  2014.7    88.3 2008.65
     134 1995.32   156.9 1987.29   173.3 1980.73   196.2    1970     206 1965.14
  215.881958.189   245.1 1957.05  256.29 1954.57     271 1952.24   280.7 1954.56
   287.2 1955.89   296.8 1954.93   309.9 1956.27   339.3 1956.91  355.851959.176
   411.2 1975.96   437.3 1980.27  454.271980.847   515.7 1984.05   594.1 1986.32
  621.721990.308   659.5 1995.47  688.04  1997.6   742.8  2002.8   767.3 2005.51
#Mann= 9 ,-1 , 0
       0     .12       0  215.88    .016       0  256.29    .045       0
   280.7     .12       0  355.85     .06       0  454.27     .12       0
  621.72     .06       0  688.04     .12       0   742.8     .06       0
#XS Ineff= 2 , 0
                          323.63         1959.05
Permanent Ineff=
       F       F
Bank Sta=256.29,280.7
XS Rating Curve= 0 ,0
Exp/Cntr=0.3,0.1

Type RM Length L Ch R = 1 ,119.3   ,117,119.3,121.5
XS GIS Cut Line= 3
     1952551.287      204760.472     1952187.789      204872.235
     1951943.649      204824.492
#Sta/Elev= 30
       0 2048.71    36.1 2032.23      59 2020.19    68.8 2013.66    72.1 2012.38
      82 2010.97    91.8 2006.48   104.9 2001.97   150.8 1988.96   173.8 1979.55
  206.331963.318   213.1 1958.61   216.4  1957.6   229.5 1957.26  239.551954.667
   249.2 1953.14     259 1951.13   272.1 1952.01   275.4 1953.06   281.9 1954.94
  314.01  1955.5  334.931956.378   354.1 1958.67   363.9 1962.59   445.8 1985.67
   481.8 1997.59   517.8 2011.13   527.6 2013.08  559.642022.058   629.1 2043.49
#Mann= 8 ,-1 , 0
       0     .12       0  206.33    .016       0  239.55     .12       0
   249.2    .045       0   275.4     .12       0  314.01     .06       0
  334.93     .12       0  559.64     .06       0
Bank Sta=249.2,275.4
XS Rating Curve= 0 ,0
Exp/Cntr=0.3,0.1

Chan Stop Cuts=-1
Use User Specified Reach Order=0
Composite Channel Slope=5